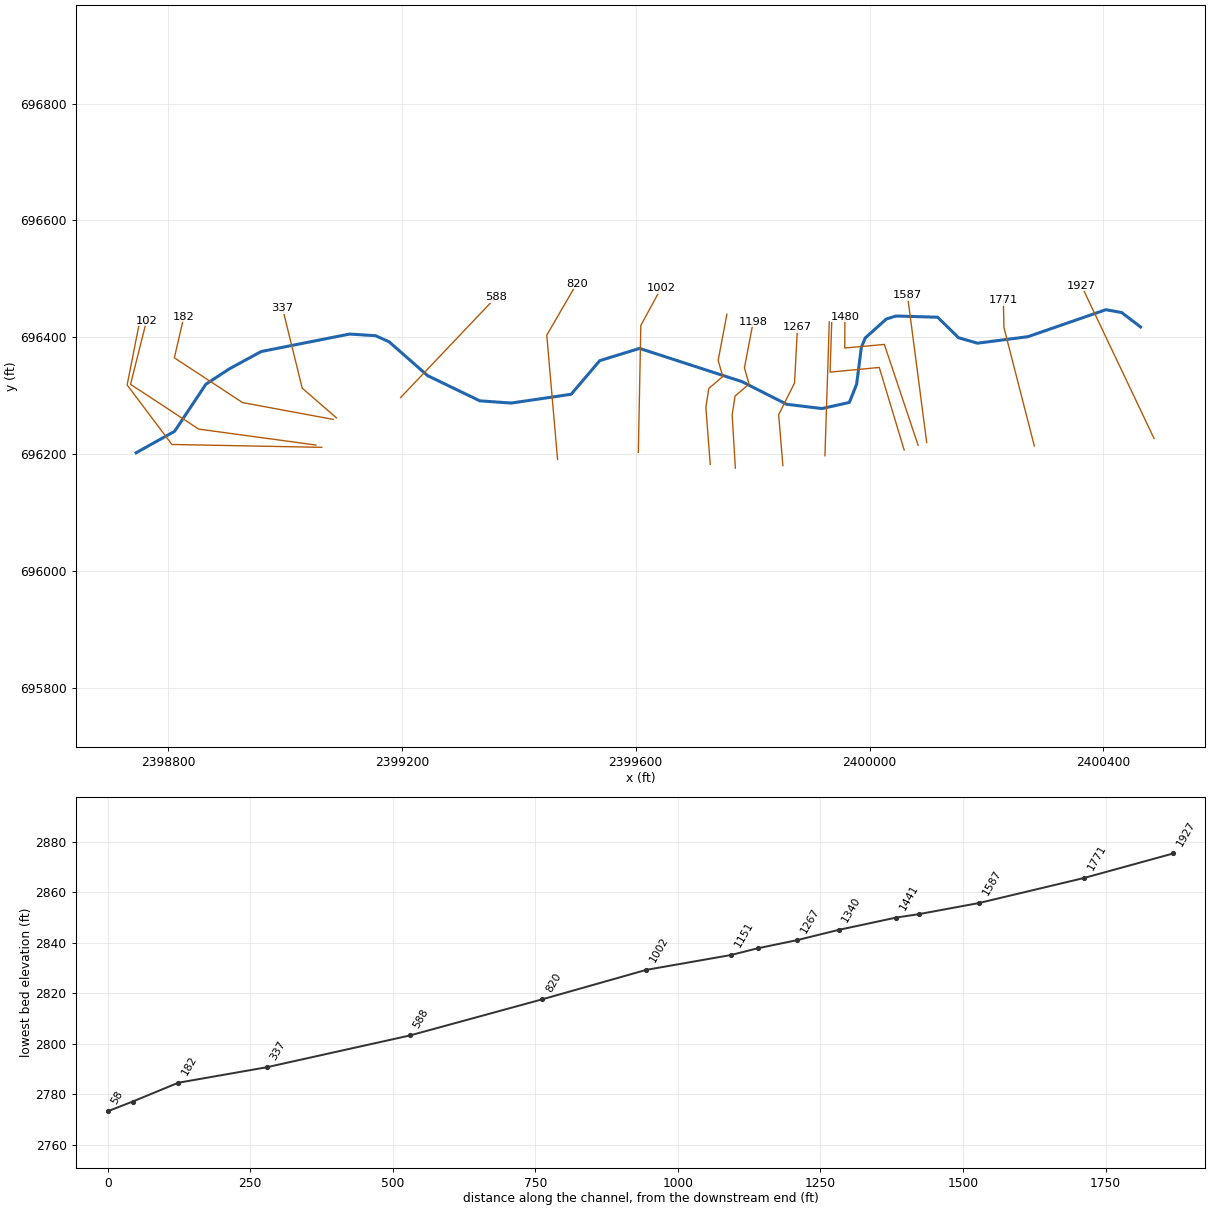
--- HRSCMPRNT1.prj (project) ---

Proj Title=HRSCMPRNT1
Current Plan=p01
Default Exp/Contr=0,0
English Units
Geom File=g01
Flow File=f01
Plan File=p01
BEGIN DESCRIPTION:
----------MODEL BY WOOD PLC 2022----------
AFH study
Randolph County, WV
HEC-RAS Version: RAS 6.2
Vertical Datum: NAVD88
Projection: NAD 1983 StatePlane West Virginia S FIPS 4702 (US Feet)
Terrain: 1-meter LIDAR (FEMA Region III 3DEP collected 2016-2018)
Land Use: 2019 NLCD
Hydrologic Method:
WV SIR2010-5033 regression equations
Additional Model Notes:
None
END DESCRIPTION:
DSS Export Rating Curves= 0
DSS Export Rating Curve Sorted= 0
DSS Export Volume Flow Curves= 0
DXF OffsetX= 0
DXF OffsetY= 0
DXF ScaleX= 0
DXF ScaleY= 0

--- HRSCMPRNT1.p01 (plan) ---

Plan Title=Floodplain
Program Version=6.20
Short Identifier=Floodplain
Geom File=g01
Flow File=f01
Subcritical Flow
K Sum by GR= 0
Std Step Tol= 0.01
Critical Tol= 0.01
Num of Std Step Trials= 20
Max Error Tol= 0.3
Flow Tol Ratio= 0.001
Split Flow NTrial= 30
Split Flow Tol= 0.02
Split Flow Ratio= 0.02
Log Output Level= 0
Friction Slope Method= 1
Unsteady Friction Slope Method= 2
Unsteady Bridges Friction Slope Method= 1
Parabolic Critical Depth
Global Vel Dist= 0 , 0 , 0
Global Log Level= 0
CheckData=True
Encroach Param=-1 ,0,0, 0
Mapping Interval=1HOUR
Computation Time Step Use Courant=        0
Computation Time Step Use Time Series=    0
Computation Time Step Count To Double=0
Computation Time Step Max Doubling=0
Computation Time Step Max Halving=0
Computation Time Step Residence Courant=0
Run HTab= 0
Run UNet= 0
Run Sediment= 0
Run PostProcess= 0
Run WQNet= 0
Run RASMapper=-1
UNET Theta= 0
UNET Theta Warmup= 0
UNET ZTol= 0
UNET ZSATol= 0
UNET MxIter= 0
UNET Max Iter WO Improvement= 0
UNET MaxInSteps= 0
UNET DtIC= 0
UNET DtMin= 0
UNET MaxCRTS= 0
UNET WFStab= 0
UNET SFStab= 0
UNET WFX= 1
UNET SFX= 1
UNET Gravity=32.174
UNET 1D Methodology=Finite Difference
UNET DSS MLevel= 1
UNET Pardiso=0
UNET DZMax Abort= 0
UNET Use Existing IB Tables= 0
UNET Froude Reduction=False
UNET Froude Limit= 0
UNET Froude Power= 0
UNET D1 Cores= 0
UNET WindReference=Eulerian
UNET WindDragFormulation=Hsu (1988)
UNET D2 Coriolis=0
UNET D2 Cores= 0
UNET D2 Theta= 1
UNET D2 Theta Warmup= 1
UNET D2 Z Tol= 0.01
UNET D2 Volume Tol= 0.01
UNET D2 Max Iterations= 20
UNET D2 Equation= 0
UNET D2 RampUpFraction=0.1
UNET D2 TimeSlices= 1
UNET D2 Turbulence Formulation=Non-Conservative (original)
UNET D2 Eddy Viscosity=0.3
UNET D2 Transverse Eddy Viscosity=0.1
UNET D2 Smagorinsky Mixing=0
UNET D2 BCVolumeCheck=0
UNET D2 Cores=0
UNET D2 SolverType=PARDISO (Direct)
UNET D2 Minimum Iterations= 2147483647
UNET D2 Maximum Iterations= 2147483647
UNET D2 Restart Number= 10
UNET D2 Relaxation Coeff=1.3
UNET D2 SOR Precondition Iterations= 10
UNET D2 ILUT Maximum Fill= 8
UNET D2 ILUT Tolerance=1E-08
UNET D1D2 MaxIter= 0
UNET D1D2 ZTol=0.01
UNET D1D2 QTol=0.1
UNET D1D2 MinQTol=1
Write IC File= 0
Write IC File at Fixed DateTime=0
Write IC File at Sim End=0
Echo Input=False
Echo Parameters=False
Echo Output=False
Write Detailed= 0
HDF Write Warmup=0
HDF Write Time Slices=0
HDF Flush=0
HDF Compression= 1
HDF Chunk Size= 1
HDF Spatial Parts= 1
HDF Use Max Rows=0
HDF Fixed Rows= 1
Calibration Method= 0
Calibration Iterations= 20
Calibration Max Change=0.05
Calibration Tolerance=0.2
Calibration Maximum=1.5
Calibration Minimum=0.5
Calibration Optimization Method= 1
WQ AD Non Conservative
WQ ULTIMATE=-1
WQ Max Comp Step=1HOUR
WQ Output Interval=15MIN
WQ Output Selected Increments= 0
WQ Output face flow=0
WQ Output face velocity=0
WQ Output face area=0
WQ Output face dispersion=0
WQ Output cell volume=0
WQ Output cell surface area=0
WQ Output cell continuity=0
WQ Output cumulative cell continuity=0
WQ Output face conc=0
WQ Output face dconc_dx=0
WQ Output face courant=0
WQ Output face peclet=0
WQ Output face adv mass=0
WQ Output face disp mass=0
WQ Output cell mass=0
WQ Output cell source sink temp=0
WQ Output nsm pathways=0
WQ Output nsm derived pathways=0
WQ Create Restart=0
WQ Fixed Restart=0
WQ System Summary=0
WQ Write To DSS=0
Sorting and Armoring Iterations= 10
XS Update Threshold= 0.02
Bed Roughness Predictor= 0
Hydraulics Update Threshold= 0.02
Energy Slope Method= 1
Volume Change Method= 1
Sediment Retention Method= 0
Sediment TS Multiplier= 1
Warm Up Method= 0
XS Weighting Method= 0
Number of US Weighted Cross Sections= 1
Number of DS Weighted Cross Sections= 1
Upstream XS Weight=0
Main XS Weight=1
Downstream XS Weight=0
Number of DS XS's Weighted with US Boundary= 1
Upstream Boundary Weight= 1
Weight of XSs Associated with US Boundary= 0
Number of US XS's Weighted with DS Boundary= 1
Downstream Boundary Weight= 0.5
Weight of XSs Associated with DS Boundary= 0.5
Percentile Method= 0
Sediment Output Level= 3
Mass or Volume Output= 0
Output Increment Type= 1
Profile and TS Output Increment= 1
Transport Output Increment 1
XS Output Flag= 0
XS Output Increment= 10
Read HDF5 Sediment Hotstart= 0
Sediment Hotstart Type= 0
Write Gradation File= 0
Read Gradation Hotstart= 0
Write HDF5 File= 1
Write Binary Output= 1
Write DSS Sediment File= 0
DSS Sediment Output Type= 1
SV Curve= 0
Specific Gage Flag= 0
Subcell Erosion Methods= 0
Subcell Deposition Methods= 0
Advection Scheme= 1
Matrix Solver= 0
Implicit Weighting Factor= 1
Maximum Outer Loop Convergence Iterations= 5
Convergence Maximum Absolute= 0.001
Convergence RMSE= 0.0001
Grain Fractions Max Abs Error= 0.001
Max Subgrid Regions= 1
Max Subgrid Length Scale= 3.402823E+38
Initial Layer Thickness= 3.402823E+38
Min Layer Thickness= 3.402823E+38
Max Layer Thickness= 3.402823E+38
Number of Layers= 5

--- HRSCMPRNT1.f01 (steady flow) ---

Flow Title=Flow
Program Version=6.20
Number of Profiles= 1
Profile Names=P100yr
River Rch & RM=HRSCMPRNT1,Main,1927
     378
Boundary for River Rch & Prof#=HRSCMPRNT1,Main            , 1
Up Type= 0
Dn Type= 3
Dn Slope=0.08871
DSS Import GetInterval= 0
DSS Import GetPeak= 0
DSS Import FillOption= 0

--- HRSCMPRNT1.g01 (geometry) ---

Geom Title=Geometry
Program Version=6.20

River Reach=HRSCMPRNT1      ,Main
Reach XY= 30
2400463.75100002696417.8370000122400431.46000004696442.489999995
2400404.37600002696447.350999996     2400271.043696401.170000002
2400184.58499998      696390.0592400152.29300003      696399.434
2400116.52900001696434.5039999932400045.34899999696436.587000012
2400028.68200001696431.3790000082399992.65000002696398.975000009
2399985.97400005 696382.76700002     2399977.987696319.920000002
     2399965.487696288.6700000172399918.61199999696278.253999993
2399858.19599999696285.5450000172399781.89900002696324.224999994
2399606.56281544696381.1359093922399538.40400003696360.198000014
2399489.53013255696302.6629094172399387.01500003696287.628000006
2399333.19600001696291.4480000142399243.96000001696334.504000008
2399177.98800002696392.4899999952399154.72400001696402.906000003
2399110.27900004      696405.6842398959.23544357 696375.81530791
2398904.37600003696345.962000012  2398864.524523696319.812788796
2398811.02802818696239.311308894     2398745.266      696202.616

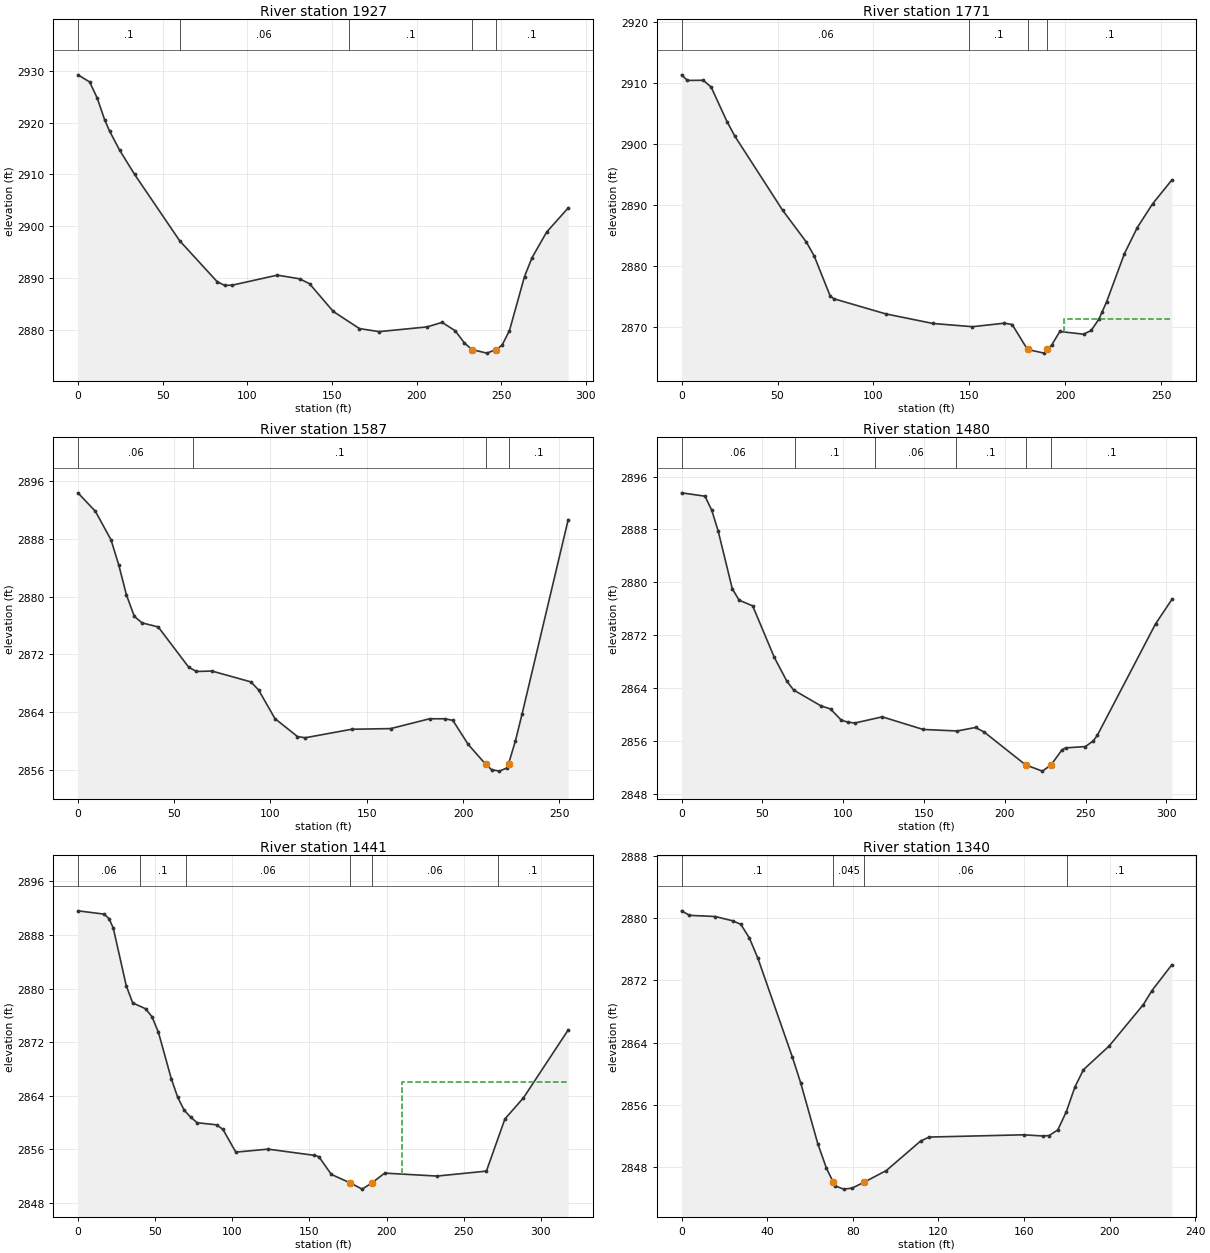
Type RM Length L Ch R = 1 ,1927    ,157.7,156.7,155.3
XS GIS Cut Line= 2
2400486.87025288 696226.917115612400362.64196113696488.477267283
#Sta/Elev= 30
       0 2929.21     6.9 2927.84    11.4 2924.72    15.8 2920.51    18.7 2918.35
    24.6 2914.68    33.5 2909.97    60.1 2897.17    82.2 2889.28    86.6 2888.56
    91.1 2888.59   117.8 2890.53   130.9 2889.82   136.8 2888.88   150.8 2883.52
   166.3 2880.21   177.9 2879.62   206.2 2880.53   215.1 2881.41   222.9 2879.78
   228.3 2877.43   232.8 2876.15   241.6 2875.47   246.9 2876.16   250.5 2876.98
   254.9 2879.82   263.8 2890.26   268.2 2893.88   276.9 2898.86   289.6 2903.51
#Mann= 5, -1 ,  0
       0     0.1       0      60    0.06       0     160     0.1       0
   232.8   0.045       0   246.9     0.1       0
Bank Sta=232.8,246.9
XS Rating Curve= 0 ,0
Exp/Cntr(USF)=0,0
Exp/Cntr=0.3,0.1

Type RM Length L Ch R = 1 ,1771    ,181.7,184,181.5
XS GIS Cut Line= 3
2400281.96964124696214.2524721632400230.00418884696416.743973641
2400228.98933269696463.201195532
#Sta/Elev= 30
       0 2911.36       3 2910.44    11.3 2910.47    15.4 2909.36    23.7 2903.68
    27.8 2901.29    52.6 2889.19      65 2883.96    69.1 2881.68    77.4 2875.14
    79.3 2874.66   106.3 2872.18     131  2870.6   151.6 2870.07   168.2 2870.65
   172.3 2870.43  180.28 2866.34   188.9 2865.74   190.72866.339     193 2867.12
   197.1 2869.29   209.5 2868.84   213.5 2869.46   217.5 2871.32   219.1 2872.44
   221.5 2874.15   230.8 2882.05   237.5 2886.33   245.5 2890.23   255.5 2894.12
#Mann= 4, -1 ,  0
       0    0.06       0     150     0.1       0  180.28   0.045       0
   190.7     0.1       0
#XS Ineff= 2 , 0
                          199.51         2871.33
Permanent Ineff=
       F       F
Bank Sta=180.28,190.7
XS Rating Curve= 0 ,0
Exp/Cntr(USF)=0,0
Exp/Cntr=0.3,0.1

Type RM Length L Ch R = 1 ,1587    ,93.1,106.1,115
XS GIS Cut Line= 2
2400097.84414378696220.1486689452400064.83614672696472.613187562
#Sta/Elev= 30
       0 2894.37     9.1  2891.8    17.2 2887.85    21.2 2884.38    25.2 2880.22
    29.3 2877.26    33.3 2876.36    41.7  2875.8    57.5 2870.23    61.5 2869.63
    69.6 2869.69    89.8 2868.19    93.8 2867.08   102.3 2863.11     114 2860.62
     118 2860.45   142.2 2861.63   162.4 2861.72   182.6 2863.08   190.6 2863.08
   194.7 2862.86   202.7 2859.52  211.69  2856.8   214.8 2856.03   218.9 2855.83
   222.9 2856.29   223.6 2856.82   227.2 2860.02   230.7  2863.8   254.6 2890.66
#Mann= 4, -1 ,  0
       0    0.06       0      60     0.1       0  211.69   0.045       0
   223.6     0.1       0
Bank Sta=211.69,223.6
XS Rating Curve= 0 ,0
Exp/Cntr(USF)=0,0
Exp/Cntr=0.3,0.1

Type RM Length L Ch R = 1 ,1480    ,40,39.1,39.5
XS GIS Cut Line= 4
  2400083.123104696215.4367298672400025.39851136696387.941741412
2399957.66657712696381.8347637352399957.93714498696435.281112012
#Sta/Elev= 30
       0 2893.53    14.5 2893.02    18.7 2890.88    22.7  2887.7    31.4 2878.99
    35.6 2877.28      44 2876.41    57.4 2868.61    65.1 2865.03    69.3 2863.68
    86.2 2861.28    92.2  2860.8    98.9 2859.09   103.1  2858.8   107.3 2858.68
   124.2 2859.61   149.5  2857.7   170.6 2857.47   181.9    2858   187.2 2857.32
   212.92852.339   223.3 2851.39   228.7 2852.34   235.3 2854.58   237.6 2854.91
   249.9 2855.11   254.8 2855.97   257.3 2856.82   293.3 2873.68   303.4 2877.38
#Mann= 6, -1 ,  0
       0    0.06       0      70     0.1       0     120    0.06       0
     170     0.1       0   212.9   0.045       0   228.7     0.1       0
Bank Sta=212.9,228.7
XS Rating Curve= 0 ,0
Exp/Cntr(USF)=0,0
Exp/Cntr=0.3,0.1

Type RM Length L Ch R = 1 ,1441    ,113.3,101.3,89.7
XS GIS Cut Line= 4
2400059.31676681696207.2132761282400016.65724138696348.515400151
2399932.51750241696340.597525309 2399935.3570438696426.147106161
#Sta/Elev= 30
       0  2891.6    16.9 2891.11    20.1 2890.45    22.9 2889.04    31.3 2880.43
    35.5 2877.85    43.8 2876.99      48 2875.79    52.2 2873.44    60.5 2866.54
    64.7 2863.74    68.9 2861.83    73.1 2860.79    77.3 2859.97    89.8 2859.66
      94 2858.97   102.3 2855.58   123.2 2856.03   153.3  2855.1   156.1 2854.91
   164.2 2852.26   176.62850.967   184.2 2850.06   190.32850.958   198.8 2852.45
   232.7 2852.01   264.7 2852.75   276.7 2860.54   288.7 2863.68   317.7 2873.82
#Mann= 6, -1 ,  0
       0    0.06       0      40     0.1       0      70    0.06       0
   176.6   0.045       0   190.3    0.06       0  272.11     0.1       0
#XS Ineff= 2 , 0
                          209.92         2866.02
Permanent Ineff=
       F       F
Bank Sta=176.6,190.3
XS Rating Curve= 0 ,0
Exp/Cntr(USF)=0,0
Exp/Cntr=0.3,0.1

Type RM Length L Ch R = 1 ,1340    ,76.5,73.1,69.7
XS GIS Cut Line= 2
 2399923.7152378696197.5105184692399931.15955389696426.495658636
#Sta/Elev= 30
       0 2880.92     3.7 2880.34    15.7 2880.19      24 2879.63    27.7 2879.18
    31.7 2877.42    35.7  2874.8    51.7 2862.19    55.7 2858.78    63.7 2850.96
    67.7 2847.85   70.862846.065    71.7 2845.59    75.7 2845.16    79.7 2845.29
   85.392846.063    95.7 2847.55   111.7 2851.34   115.7 2851.85   159.8 2852.14
   168.8 2851.99   171.8 2852.05   175.8 2852.77   179.8 2855.11   183.8 2858.28
   187.8 2860.51   199.8 2863.55   215.8 2868.88   219.8 2870.67   229.1 2873.99
#Mann= 4, -1 ,  0
       0     0.1       0   70.86   0.045       0   85.39    0.06       0
     180     0.1       0
Bank Sta=70.86,85.39
XS Rating Curve= 0 ,0
Exp/Cntr(USF)=0,0
Exp/Cntr=0.3,0.1

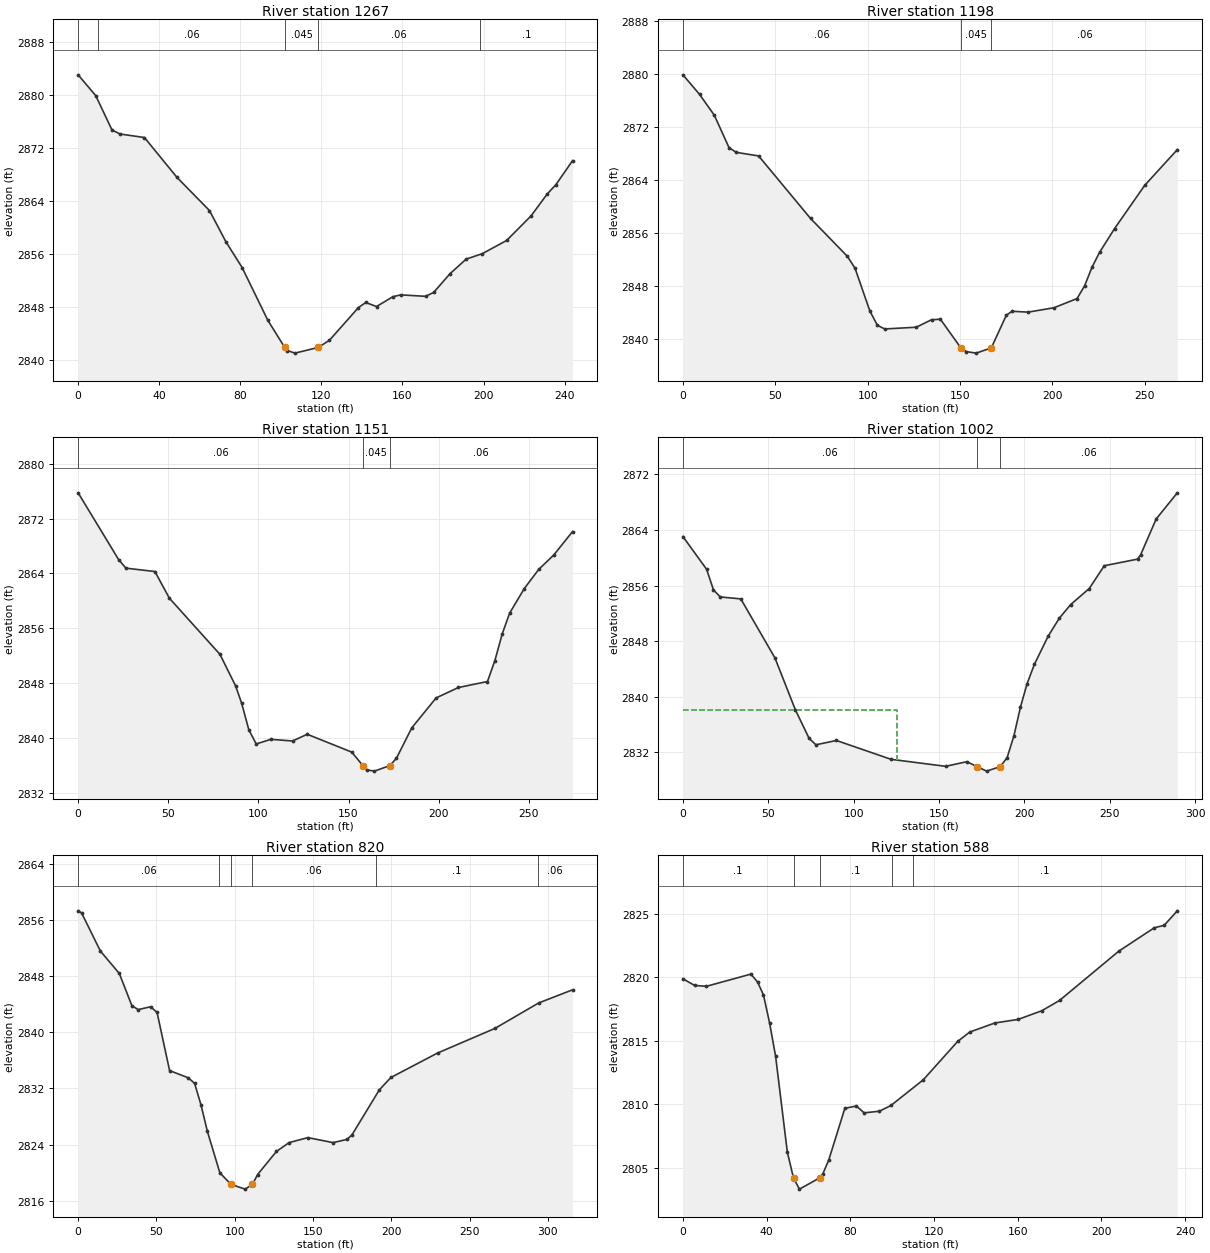
Type RM Length L Ch R = 1 ,1267    ,68.6,68.8,72.7
XS GIS Cut Line= 4
2399851.76884408696180.5510121652399844.55150683696267.714239018
2399871.75531648696322.1218583282399876.75193458696417.612782014
#Sta/Elev= 30
       0 2883.08     8.7 2879.93    16.7 2874.76    20.7 2874.15    32.7 2873.62
    48.8 2867.59    64.8  2862.6    72.9 2857.89    80.9    2854    93.6 2846.03
  101.912841.954   103.2 2841.48     107 2841.09  118.492841.956     124 2843.04
   138.3 2847.97   141.9 2848.73   147.2 2848.12   155.3 2849.61   159.2 2849.88
   171.4 2849.66   175.4 2850.25   183.4 2853.06   191.4 2855.27   199.4  2856.1
   211.4 2858.09   223.5 2861.82   231.5 2865.14   235.6 2866.47   243.9 2870.13
#Mann= 5, -1 ,  0
       0     0.1       0      10    0.06       0  101.91   0.045       0
  118.49    0.06       0  198.29     0.1       0
Bank Sta=101.91,118.49
XS Rating Curve= 0 ,0
Exp/Cntr(USF)=0,0
Exp/Cntr=0.3,0.1

Type RM Length L Ch R = 1 ,1198    ,46.8,46.9,46.6
XS GIS Cut Line= 6
2399770.47483948696176.2140838712399764.97855958696267.152533289
2399769.97517768696299.6305509382399793.95894455696320.116685147
2399785.96435559696347.5980846962399800.95420989696426.544650674
#Sta/Elev= 30
       0  2879.9       9 2876.95      17  2873.8      25 2868.88      29 2868.19
      41 2867.65    69.1 2858.21    89.1 2852.48    93.2 2850.69   101.2 2844.25
   105.3 2842.08   109.3 2841.53   126.3 2841.79   134.6 2842.92   139.4    2843
   150.52838.673   153.4 2838.11   158.8 2837.88  166.982838.675   175.1  2843.6
   178.2  2844.2   186.9 2844.07   200.9 2844.73   213.4 2846.12   217.5 2848.05
   221.5 2850.85   225.6  2853.1   233.7 2856.68     250  2863.2   267.7 2868.61
#Mann= 3, -1 ,  0
       0    0.06       0   150.5   0.045       0  166.98    0.06       0
Bank Sta=150.5,166.98
XS Rating Curve= 0 ,0
Exp/Cntr(USF)=0,0
Exp/Cntr=0.3,0.1

Type RM Length L Ch R = 1 ,1151    ,146.8,148.8,149.1
XS GIS Cut Line= 6
2399727.50392383696182.7096874012399720.00899668696280.143740348
2399725.00561478696312.6217579982399748.98938166696333.107892207
 2399740.9947927696360.589291756  2399755.984647696439.535857734
#Sta/Elev= 30
       0 2875.74    22.5    2866    26.5 2864.77    42.6 2864.28    50.6  2860.4
    78.7 2852.21    87.4  2847.6    90.7 2845.11    94.7 2841.23    98.8 2839.16
   106.9 2839.84     119  2839.6   127.1 2840.58   151.8 2837.98  157.932836.027
     160  2835.4   164.4 2835.21  173.052836.028   176.6 2837.09   185.1 2841.51
   198.6 2845.87     211 2847.39   227.1 2848.26   231.2  2851.3   235.3 2855.21
   239.4 2858.22   247.5 2861.79   255.6 2864.61   263.8 2866.66   274.3  2870.1
#Mann= 3, -1 ,  0
       0    0.06       0  157.93   0.045       0  173.05    0.06       0
Bank Sta=157.93,173.05
XS Rating Curve= 0 ,0
Exp/Cntr(USF)=0,0
Exp/Cntr=0.3,0.1

Type RM Length L Ch R = 1 ,1002    ,182.2,182.1,183.5
XS GIS Cut Line= 3
2399604.45082212696203.3094249472399608.74340261696420.459176356
2399643.26545373696484.074389216
#Sta/Elev= 30
       0 2863.06    13.9 2858.34    17.9 2855.38    21.9 2854.37    33.9 2854.09
    53.9  2845.6    65.9 2838.11    73.9 2834.03    77.9  2833.1    89.9 2833.72
   121.9 2831.01   153.9    2830   166.3 2830.67  172.24 2829.96   177.9 2829.31
   185.9 2829.96   189.9 2831.25   193.9 2834.41   197.7 2838.52   201.6 2841.89
   205.9 2844.69   213.9 2848.71   220.4 2851.29   227.1 2853.27     238 2855.58
   246.8 2858.86   266.3 2859.81   268.1 2860.43   277.2 2865.59   289.6 2869.35
#Mann= 3, -1 ,  0
       0    0.06       0  172.24   0.045       0   185.9    0.06       0
#XS Ineff= 2 , 0
          125.37 2838.07
Permanent Ineff=
       F       F
Bank Sta=172.24,185.9
XS Rating Curve= 0 ,0
Exp/Cntr(USF)=0,0
Exp/Cntr=0.3,0.1

Type RM Length L Ch R = 1 ,820     ,237.2,231.9,226.3
XS GIS Cut Line= 3
2399466.25590941 696191.016619882399447.79016715696403.811013324
2399499.07448248696492.131036279
#Sta/Elev= 30
       0 2857.27     2.2 2856.97    14.2 2851.55    26.3 2848.35    34.3 2843.78
    38.3 2843.21    46.3 2843.62    50.4  2842.8    58.4 2834.53    70.4  2833.5
    74.4  2832.7    78.5 2829.61    82.5  2825.9    90.5 2819.98   97.59 2818.34
   106.6 2817.66  111.31 2818.33   114.6 2819.74   126.6 2823.02   134.7 2824.28
   146.7 2824.99   162.8 2824.28   171.6 2824.73   174.8 2825.36   192.3 2831.78
   199.7 2833.55   229.5 2837.03   266.1 2840.53     294 2844.15   315.7 2846.03
#Mann= 6, -1 ,  0
       0    0.06       0      90     0.1       0   97.59   0.045       0
  111.31    0.06       0     190     0.1       0  293.59    0.06       0
Bank Sta=97.59,111.31
XS Rating Curve= 0 ,0
Exp/Cntr(USF)=0,0
Exp/Cntr=0.3,0.1

Type RM Length L Ch R = 1 ,588     ,245.3,251.6,257.2
XS GIS Cut Line= 2
2399197.78322329696297.0872875652399360.55239656696468.450624902
#Sta/Elev= 30
       0 2819.87     5.6 2819.35    11.2 2819.28    32.5 2820.24    35.7 2819.61
    38.5  2818.6    41.4 2816.42    44.3 2813.78    49.9 2806.26   52.85 2804.22
    55.7 2803.35    65.32804.231    66.8 2804.52    69.7 2805.64    77.4  2809.7
    82.9 2809.88    86.6 2809.34    93.9 2809.47    99.4 2809.92   114.9 2811.94
   131.3 2814.95   137.1 2815.69   149.1  2816.4   160.2 2816.68   171.5 2817.36
     180 2818.17   208.3 2822.04   225.3 2823.88     230 2824.07   236.3 2825.21
#Mann= 5, -1 ,  0
       0     0.1       0   52.85   0.045       0    65.3     0.1       0
     100    0.05       0     110     0.1       0
Bank Sta=52.85,65.3
XS Rating Curve= 0 ,0
Exp/Cntr(USF)=0,0
Exp/Cntr=0.3,0.1

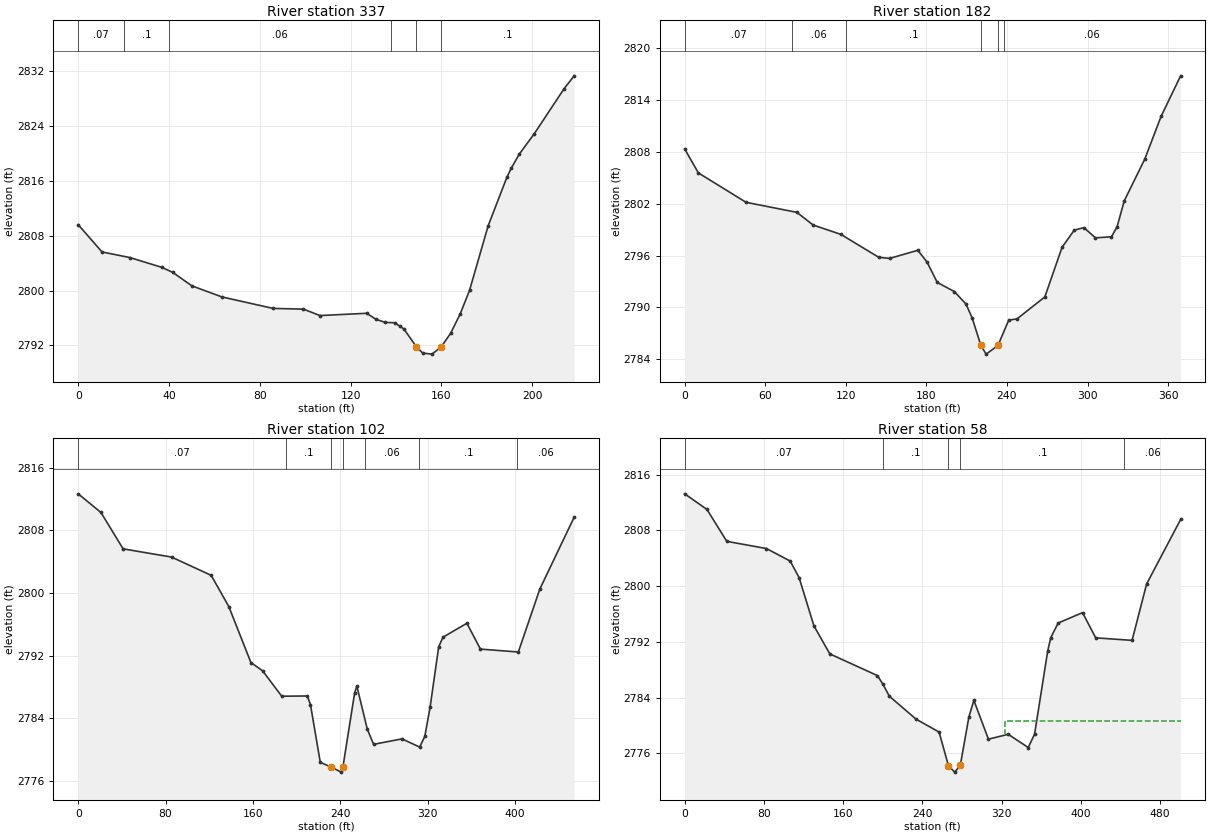
Type RM Length L Ch R = 1 ,337     ,151.1,154.9,160.1
XS GIS Cut Line= 3
2399087.94715116696262.2772149352399029.35197505696313.136802602
2398995.64757157696449.991683448
#Sta/Elev= 30
       0 2809.62    10.5 2805.64    22.7 2804.83    36.8  2803.4    41.6 2802.67
    50.1 2800.69    63.3 2799.08    85.9  2797.4    99.2  2797.3   106.5 2796.36
   127.1 2796.69   131.2 2795.81   135.3 2795.36   139.4 2795.31   141.6 2794.83
   143.5  2794.4  148.952791.817   151.8 2790.88   155.9 2790.73  160.012791.815
   164.1 2793.79   168.3  2796.6   172.4 2800.03   180.6 2809.45   188.9 2816.57
   190.8 2817.87   194.3 2819.91   200.9 2822.88   214.1 2829.49   218.5 2831.35
#Mann= 6, -1 ,  0
       0    0.07       0      20     0.1       0      40    0.06       0
  137.59     0.1       0  148.95   0.045       0  160.01     0.1       0
Bank Sta=148.95,160.01
XS Rating Curve= 0 ,0
Exp/Cntr(USF)=0,0
Exp/Cntr=0.3,0.1

Type RM Length L Ch R = 1 ,182     ,80.1,80.3,80
XS GIS Cut Line= 4
2399082.24856736696259.6840925292398927.17012753696288.485787341
2398810.59764154696365.0935823982398826.92138246696435.342977728
#Sta/Elev= 30
       0 2808.33    10.2 2805.56    45.7 2802.16    83.5    2801    95.7 2799.53
   116.3 2798.45   144.5  2795.8   152.6 2795.67   173.6 2796.61   180.5 2795.24
   188.1 2792.89   200.8 2791.84   209.5 2790.39     214 2788.82  220.572785.601
   224.5  2784.6  233.282785.602   241.3 2788.53   247.5 2788.68   268.2 2791.22
     281 2796.95   290.1 2798.94   297.3 2799.23   305.9 2798.05   317.8 2798.17
     322 2799.33   327.3 2802.32   342.5 2807.12   354.8 2812.11   369.3 2816.79
#Mann= 6, -1 ,  0
       0    0.07       0      80    0.06       0     120     0.1       0
  220.57   0.045       0  233.28     0.1       0  237.73    0.06       0
Bank Sta=220.57,233.28
XS Rating Curve= 0 ,0
Exp/Cntr(USF)=0,0
Exp/Cntr=0.3,0.1

Type RM Length L Ch R = 1 ,102     ,45.2,43.4,41.3
XS GIS Cut Line= 4
 2399052.7845178696215.7815074592398852.23685326696243.084216842
2398735.66436727696319.6920118992398762.98066801696428.415366597
#Sta/Elev= 30
       0 2812.68    20.8  2810.3    41.1 2805.65    85.4  2804.6   121.7 2802.27
   137.9 2798.26   158.1 2791.12   168.8 2790.07   186.3 2786.82   209.7 2786.85
   212.6 2785.76   221.6 2778.37   231.2 2777.79   240.8 2777.12  242.34 2777.79
   253.1 2787.28   255.1  2788.1   264.6 2782.63   270.4 2780.67   296.4 2781.37
   312.6 2780.32   317.3  2781.7   322.1 2785.39     330 2793.13   333.9 2794.36
   355.8 2796.14   368.2 2792.84   402.9 2792.47   422.6 2800.52     454 2809.69
#Mann= 7, -1 ,  0
       0    0.07       0     190     0.1       0   231.2   0.045       0
  242.34     0.1       0   262.4    0.06       0   312.4     0.1       0
  401.89    0.06       0
Bank Sta=231.2,242.34
XS Rating Curve= 0 ,0
Exp/Cntr(USF)=0,0
Exp/Cntr=0.3,0.1

Type RM Length L Ch R = 1 ,58      ,,,
XS GIS Cut Line= 4
2399062.69709227696211.8812917482398806.41706957696216.779121425
2398729.81970982696318.5331501492398752.45006045696433.200793845
#Sta/Elev= 30
       0 2813.25    22.5 2811.01    42.5 2806.43    82.5  2805.4   106.5  2803.6
   115.5 2801.23   130.5 2794.29   146.5 2790.28   194.6 2787.16     200 2785.95
   206.6  2784.2   233.7  2780.9   256.8 2779.06  266.252774.237   272.5 2773.31
   278.2 2774.27   286.9 2781.24   291.9 2783.61   306.6 2778.04   326.6 2778.74
   346.8 2776.84   353.2 2778.77   366.5 2790.75   369.6 2792.63     377 2794.71
   401.6  2796.2   414.9 2792.58   451.6 2792.22   466.3 2800.32   500.6 2809.57
#Mann= 5, -1 ,  0
       0    0.07       0     200     0.1       0  266.25   0.045       0
   278.2     0.1       0  443.69    0.06       0
#XS Ineff= 2 , 0
                          323.48         2780.65
Permanent Ineff=
       F       F
Bank Sta=266.25,278.2
XS Rating Curve= 0 ,0
Exp/Cntr(USF)=0,0
Exp/Cntr=0.3,0.1
LCMann Table=0

Chan Stop Cuts=-1
Use User Specified Reach Order=0
Composite Channel Slope=5